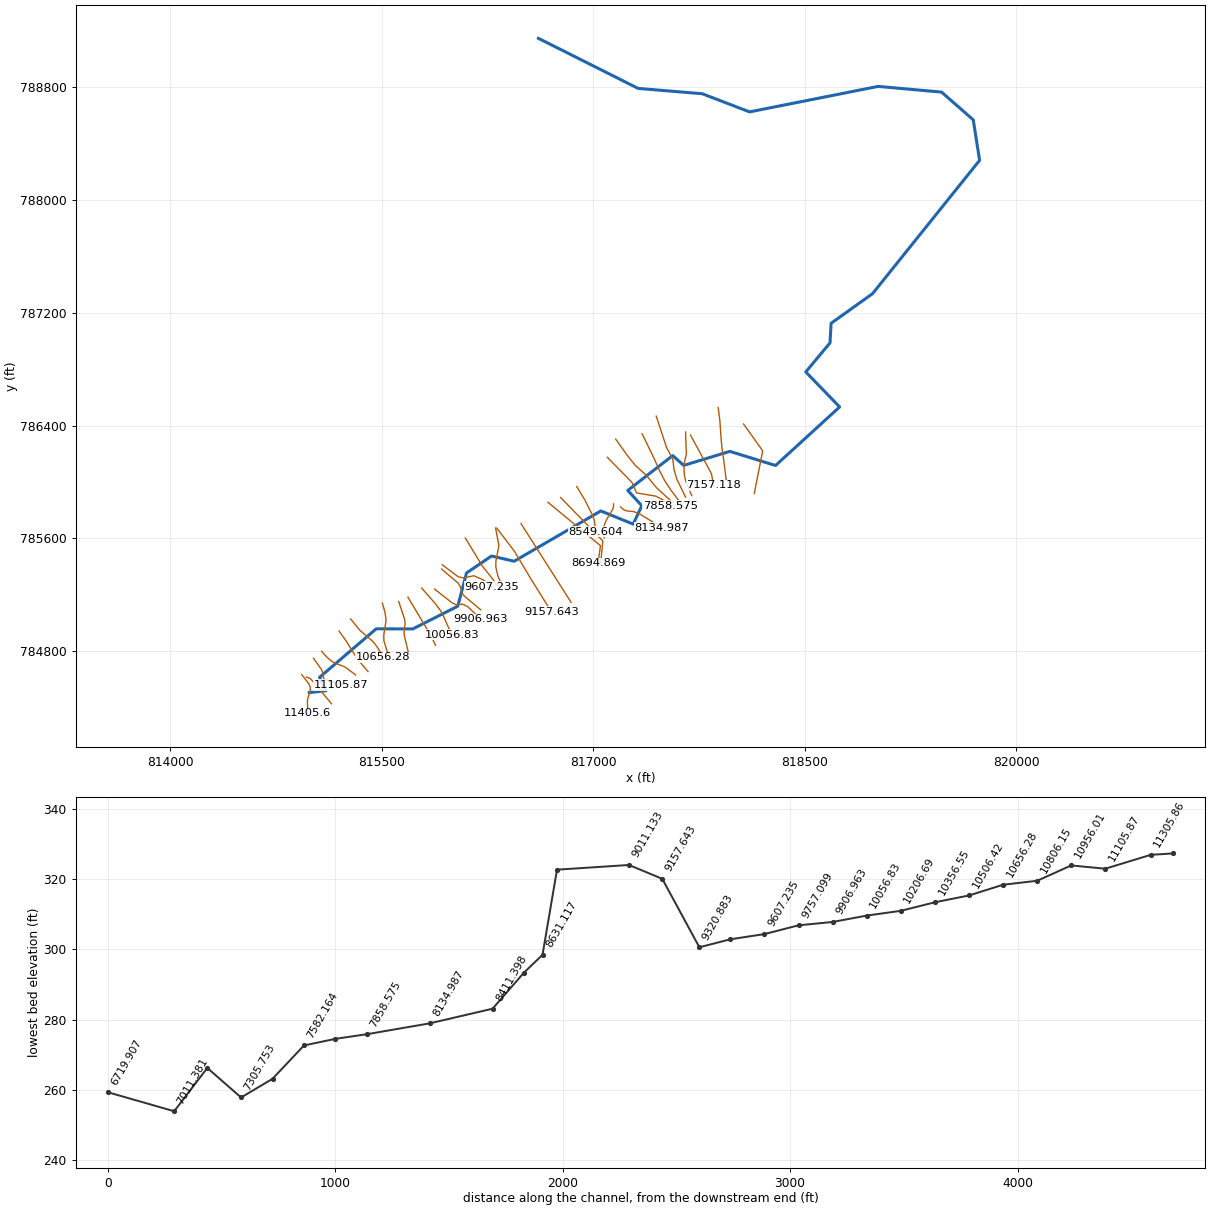
--- 17400_ras.prj (project) ---

Proj Title=17400
Current Plan=p01
Default Exp/Contr=0.3,0.1
English Units
Geom File=g01
Flow File=f01
Plan File=p01
Y Axis Title=Elevation
X Axis Title(PF)=Main Channel Distance
X Axis Title(XS)=Station
BEGIN DESCRIPTION:
RFD model 17400 exported to HEC-RAS
END DESCRIPTION:

--- 17400_ras.p01 (plan) ---

Plan Title=Plan 01
Program Version=4.10
Short Identifier=Plan 01
Geom File=g01
Flow File=f01
Subcritical Flow
Calc Critical at every XS
Secant Critical Depth

--- 17400_ras.f01 (steady flow) ---

Flow Title=Flow 01
Program Version=5.01
Number of Profiles= 6
Profile Names=10yr,25yr,50yr,100yr,100plus,500yr
River Rch & RM=17400,45, 11405.6
  140.39  227.03  308.55  384.11   560.8 1012.27
River Rch & RM=17400,45,10806.15
  171.76  278.16  378.47   471.5  688.38 1208.76
River Rch & RM=17400,45,10656.28
  175.52   284.3  386.89  482.03  703.76 1232.13
River Rch & RM=17400,45,10506.42
  187.81  304.38  414.39  516.44     754 1308.05
River Rch & RM=17400,45,10356.55
   191.5  310.41  422.65  526.77  769.09 1330.71
River Rch & RM=17400,45,10206.69
  194.07   314.6   428.4  533.98   779.6 1346.49
River Rch & RM=17400,45,10056.83
  197.34  319.97  435.75  543.19  793.06 1366.66
River Rch & RM=17400,45,9906.963
  201.68  327.08  445.52  555.43  810.92 1393.39
River Rch & RM=17400,45,9757.099
  203.85  330.62  450.38  561.52  819.82 1406.67
River Rch & RM=17400,45,9607.235
  204.57   331.8     452  563.55  822.79 1411.09
River Rch & RM=17400,45,9457.371
  206.36  334.75  456.04  568.62  830.18 1422.11
River Rch & RM=17400,45,9320.883
  209.59  340.04   463.3  577.72  843.46 1441.86
River Rch & RM=17400,45,9157.643
  211.74  343.55  468.13  583.76   852.3 1454.97
River Rch & RM=17400,45,9011.133
  216.37  351.15  478.55  596.83  871.37 1483.21
River Rch & RM=17400,45,8694.869
  221.69  359.87  490.52  611.83  893.27 1515.54
River Rch & RM=17400,45,8549.604
  224.87  365.08  497.67  620.79  906.35 1534.81
River Rch & RM=17400,45,8411.398
  226.63  367.96  501.63  625.76  913.61 1545.47
River Rch & RM=17400,45,8134.987
  315.93  514.38  702.71  877.82 1281.62 2072.49
River Rch & RM=17400,45,7858.575
  316.91  515.99  704.92   880.6 1285.68 2078.18
River Rch & RM=17400,45, 7720.37
  320.83  522.42  713.77   891.7 1301.88 2100.88
River Rch & RM=17400,45,7582.164
  324.08  527.76  721.12  900.92 1315.35 2119.72
River Rch & RM=17400,45,7443.958
  328.62  535.22  731.38   913.8 1334.15    2146
River Rch & RM=17400,45,7157.118
  332.49  541.59  740.14   924.8 1350.21 2168.42
River Rch & RM=17400,45,7011.381
  337.32  549.53  751.07  938.52 1370.24 2196.32
River Rch & RM=17400,45,6719.907
  351.46  572.76  783.02   978.6 1428.76 2277.37
River Rch & RM=17400,45,6597.842
  467.87  763.87 1045.81 1308.21 1909.98 2926.93
River Rch & RM=17400,45,6475.778
  469.07  765.84 1048.53 1311.62 1914.97 2933.55
River Rch & RM=17400,45,6353.713
  471.16  769.29 1053.28 1317.59 1923.69 2945.14
River Rch & RM=17400,45,6231.649
  472.66  771.76 1056.68 1321.86 1929.91  2953.4
River Rch & RM=17400,45,6092.923
  473.25  772.74 1058.03 1323.56  1932.4  2956.7
River Rch & RM=17400,45,5542.088
  499.36  815.75 1117.33 1398.08  2041.2 3100.61
River Rch & RM=17400,45,5401.967
   502.6  821.09 1124.69 1407.33 2054.71 3118.41
River Rch & RM=17400,45,5261.847
  503.77  823.03 1127.37  1410.7 2059.62 3124.88
River Rch & RM=17400,45,5121.726
  504.66  824.49 1129.37 1413.22  2063.3 3129.72
River Rch & RM=17400,45,4981.605
  508.18  830.29 1137.38 1423.28    2078 3149.07
Boundary for River Rch & Prof#=17400,45,1
Up Type= 0
Dn Type= 2
Boundary for River Rch & Prof#=17400,45,2
Up Type= 0
Dn Type= 2
Boundary for River Rch & Prof#=17400,45,2
Up Type= 0
Dn Type= 2
Boundary for River Rch & Prof#=17400,45,2
Up Type= 0
Dn Type= 2
Boundary for River Rch & Prof#=17400,45,2
Up Type= 0
Dn Type= 2
Boundary for River Rch & Prof#=17400,45,2
Up Type= 0
Dn Type= 2

--- 17400_ras.g01 (geometry) ---

Geom Title=17400
Program Version=4.10

River Reach=17400,45
Reach XY= 30
814984.355184794784505.637909726815103.498321712784519.134975593
815057.491377235784613.753031155815459.835127235784958.371086727
815719.383738401784957.503031156816038.828182818  785118.9613645
816100.894155026785354.638447829816278.411516131785474.864142263
816439.001793921785437.971781153817053.718674273785794.742614488
817283.530818137785701.259708515817344.739863727785831.468041849
817245.136053206785940.531432149817563.979536116786187.593397976
817642.438403606786118.037664374817969.334187388786217.533944351
818293.722633243786117.273935263818748.636415809786532.812488032
818508.316952675786781.238686246818680.253050509786987.556196349
818687.990835219787126.380457851818981.790963681 787336.33542561
819741.764314683788282.842266064819696.745423972788570.266038177
819472.192741155788766.989670157819021.323392182 788807.52160256
818109.529444188 788626.55060584817773.627158913788755.434453468
817318.862849444788793.205953323816611.133724362789148.569031601

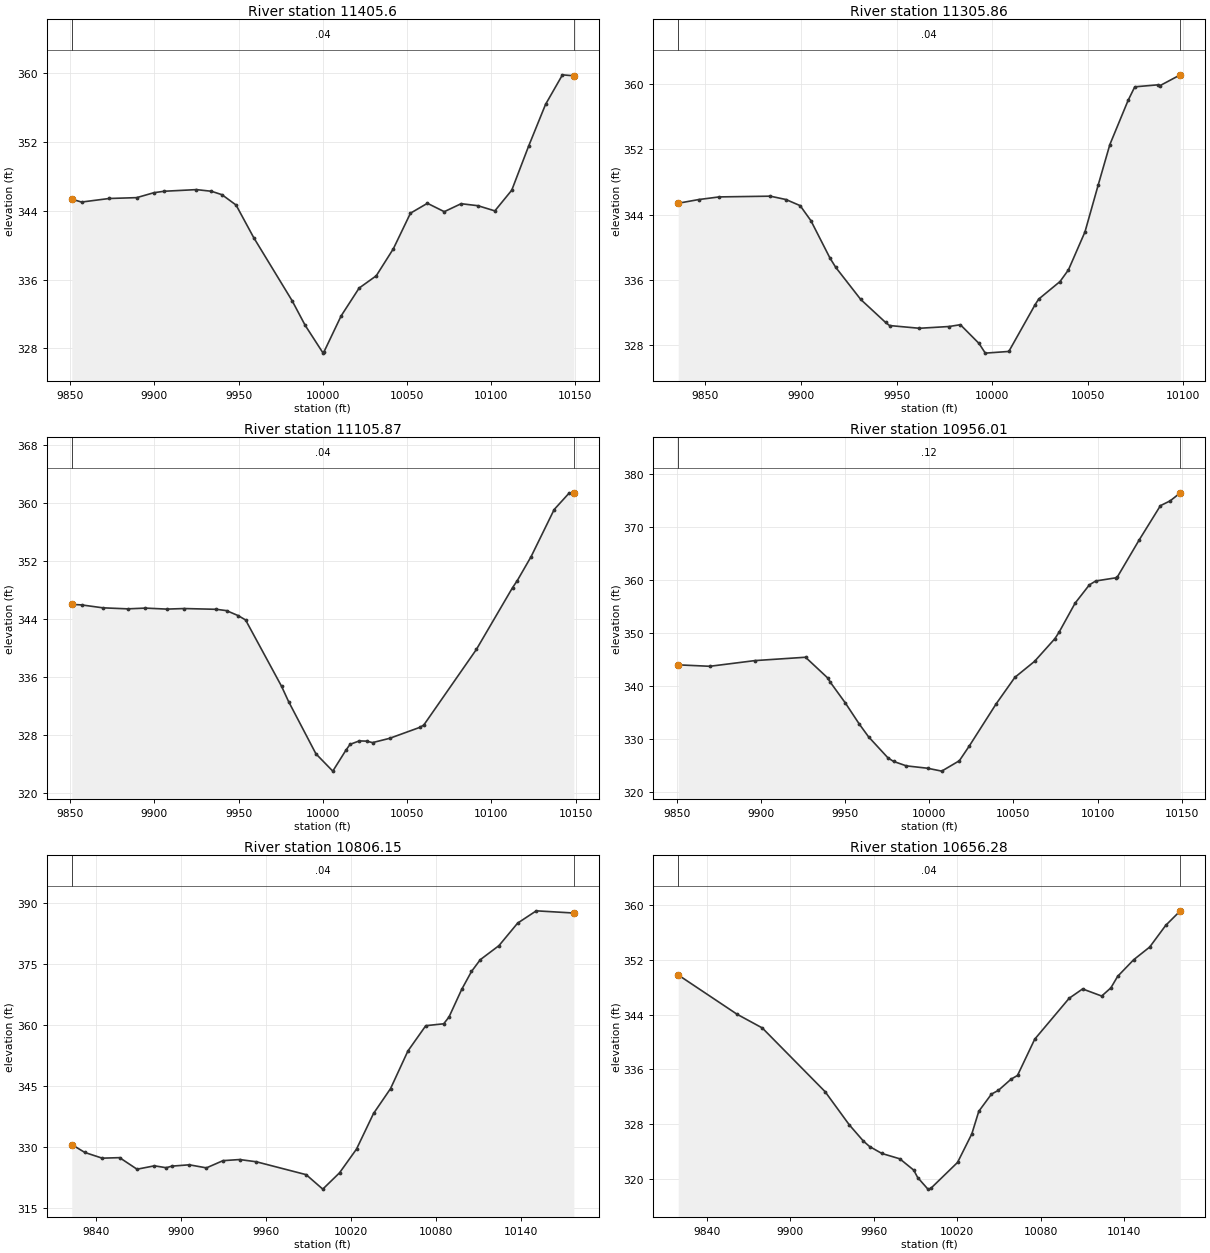
Type RM Length L Ch R = 1 , 11405.6,99.741900,99.741900,99.741900
XS GIS Cut Line= 6
814931.452882192784633.631291492814982.092493839784567.937975958
814992.639013017784541.803967471814991.394020466784522.289048435
814971.508892571 784451.52930326814974.701193677784358.257453749
#Sta/Elev= 30
9850.971345.36329856.781345.0204 9873.16 345.435 9889.54345.53499899.747346.1103
 9905.92346.2787    9925346.46879933.916346.27559940.162345.87679948.535344.6734
9958.992340.88839981.844333.53089989.573330.672710000.23327.4393 10000.6327.5303
10010.93331.775410021.61335.011310031.78336.439510041.94339.5882 10052.1343.7277
10062.16344.876510072.17343.900710082.17344.828110092.18344.5944 10102.2343.9926
10112.24346.401710122.27351.536310132.31356.388810142.35359.827210149.11359.7107
#Mann= 3 , 0 , 0
9850.971    0.04       09850.971    0.04       010149.11    0.04       0
#XS Ineff= 2 , 0
       0                               0
Bank Sta=9850.971,10149.11
Exp/Cntr=0.3,0.1

Type RM Length L Ch R = 1 ,11305.86,199.985900,199.985900,199.985900
XS GIS Cut Line= 3
814965.190817547784616.089204359814994.324299855784604.055809516
815142.525057388 784426.72156969
#Sta/Elev= 30
9835.773345.40129846.386 345.8519857.205346.17849883.941346.26879892.128345.8567
9899.536345.1101 9905.16343.2702 9915.13  338.699918.192337.53419931.225333.6134
9944.257330.78799946.318330.41169961.913330.07839977.507330.29569983.354330.5156
9993.101328.22069996.386327.0321 10008.7327.238210022.45332.970910024.29333.6483
10035.48335.807610039.88337.234510048.52341.884810055.48347.664110061.55352.5969
10071.07357.997310074.58359.669310086.67359.914410087.61359.7963 10098.4361.1408
#Mann= 3 , 0 , 0
9835.773    0.04       09835.773    0.04       0 10098.4    0.04       0
#XS Ineff= 2 , 0
       0                               0
Bank Sta=9835.773,10098.4
Exp/Cntr=0.3,0.1

Type RM Length L Ch R = 1 ,11105.87,149.864000,149.864000,149.864000
XS GIS Cut Line= 6
815014.708808657784749.605945092815071.824480554 784669.03637515
815082.241352292784641.102065666815087.784182913784599.838798349
815149.907291585 784585.43259463815207.701478367 784559.80263763
#Sta/Elev= 30
  9850.9346.01019856.722345.93839869.361345.53789884.078345.3968 9894.64345.4988
9907.279345.36239917.709345.43919936.779345.33169942.789345.15099949.793344.4545
9954.101343.86519975.446 334.7429979.607332.64969995.854 325.45310005.86323.0718
10013.55325.915310016.13326.758910021.63327.231210025.95327.197910029.46326.9956
10039.59327.582410057.55329.094210059.89329.414110091.14339.823710112.58348.3149
10115.34 349.26410123.63352.597810137.29359.060710145.96 361.26910148.97361.3579
#Mann= 3 , 0 , 0
  9850.9    0.04       0  9850.9    0.04       010148.97    0.04       0
#XS Ineff= 2 , 0
       0                               0
Bank Sta=9850.9,10148.97
Exp/Cntr=0.3,0.1

Type RM Length L Ch R = 1 ,10956.01,149.863900,149.863900,149.863900
XS GIS Cut Line= 6
815072.302375482   784798.530787815110.979483126784756.425084284
815142.990722877784729.058272886815169.045654743784714.344505306
815238.604490793784687.391113904815314.208883375784631.236985649
#Sta/Elev= 30
9850.901 344.0189869.671 343.7489896.431344.81979926.521345.45169939.677341.5536
9941.046340.8319 9950.19336.83259958.443 332.8719963.982 330.4579975.466326.5081
9978.779325.83519986.397324.9923    9999324.546310007.42324.0008 10017.9325.9573
10023.86328.765610039.77 336.67610050.89341.666210062.59344.680210074.63348.9438
10077.16350.179710086.67355.645410095.12359.0776 10098.9359.816110111.17360.4286
10111.72360.550810124.54367.448910137.35374.003510143.14374.909210149.16376.4205
#Mann= 3 , 0 , 0
9850.901    0.12       09850.901    0.12       010149.16    0.12       0
#XS Ineff= 2 , 0
       0                               0
Bank Sta=9850.901,10149.16
Exp/Cntr=0.3,0.1

Type RM Length L Ch R = 1 ,10806.15,149.863900,149.863900,149.863900
XS GIS Cut Line= 6
815196.336697779784942.479549289815249.281245703784868.203017964
815299.288684948784786.645083259815324.202821973784749.034021649
815349.588762931784716.063875309815401.925268673784654.868762778
#Sta/Elev= 30
9822.936330.59039832.122328.64649844.402327.23899856.682327.36879868.963324.5213
9881.243325.35659889.547324.89089893.524325.27919905.804325.60869917.906324.8512
9929.631326.63039941.355326.9004 9953.08326.35539988.253323.18299999.979319.6251
10011.79323.630810023.79329.484210035.78338.229310047.78344.351110060.03353.6015
10072.63359.821110085.27360.287510089.02361.964610097.94368.730210104.87373.1543
 10111.1376.063210124.26379.513710137.42385.046910150.58388.071510177.07387.5291
#Mann= 3 , 0 , 0
9822.936    0.04       09822.936    0.04       010177.07    0.04       0
#XS Ineff= 2 , 0
       09947.203                       0
Bank Sta=9822.936,10177.07
Exp/Cntr=0.3,0.1

Type RM Length L Ch R = 1 ,10656.28,149.864000,149.864000,149.864000
XS GIS Cut Line= 6
815278.119770341785028.481658053815343.897431206 784948.00877062
815425.692730598784877.895994578815446.071115085784857.452028972
815472.992034446784820.479555996815509.567112053 784755.85972571
#Sta/Elev= 30
9819.653349.80439861.939344.05929880.032342.05739925.167332.7367 9942.58327.8727
9952.697 325.5059957.132324.71379965.959323.70099978.814322.92019988.801321.2675
9991.668320.1791    9999318.4874   10001318.583410020.31322.398210030.55326.5717
10035.54 329.86810044.63332.381710049.65332.935210058.79334.577710063.35335.1099
10075.72340.414210100.46 346.39910110.12347.762610123.83346.724110130.42347.9219
10135.32349.612710146.82352.036610158.31353.8901 10169.8357.0557 10180.3359.1857
#Mann= 3 , 0 , 0
9819.653    0.04       09819.653    0.04       0 10180.3    0.04       0
#XS Ineff= 2 , 0
       0                               0
Bank Sta=9819.653,10180.3
Exp/Cntr=0.3,0.1

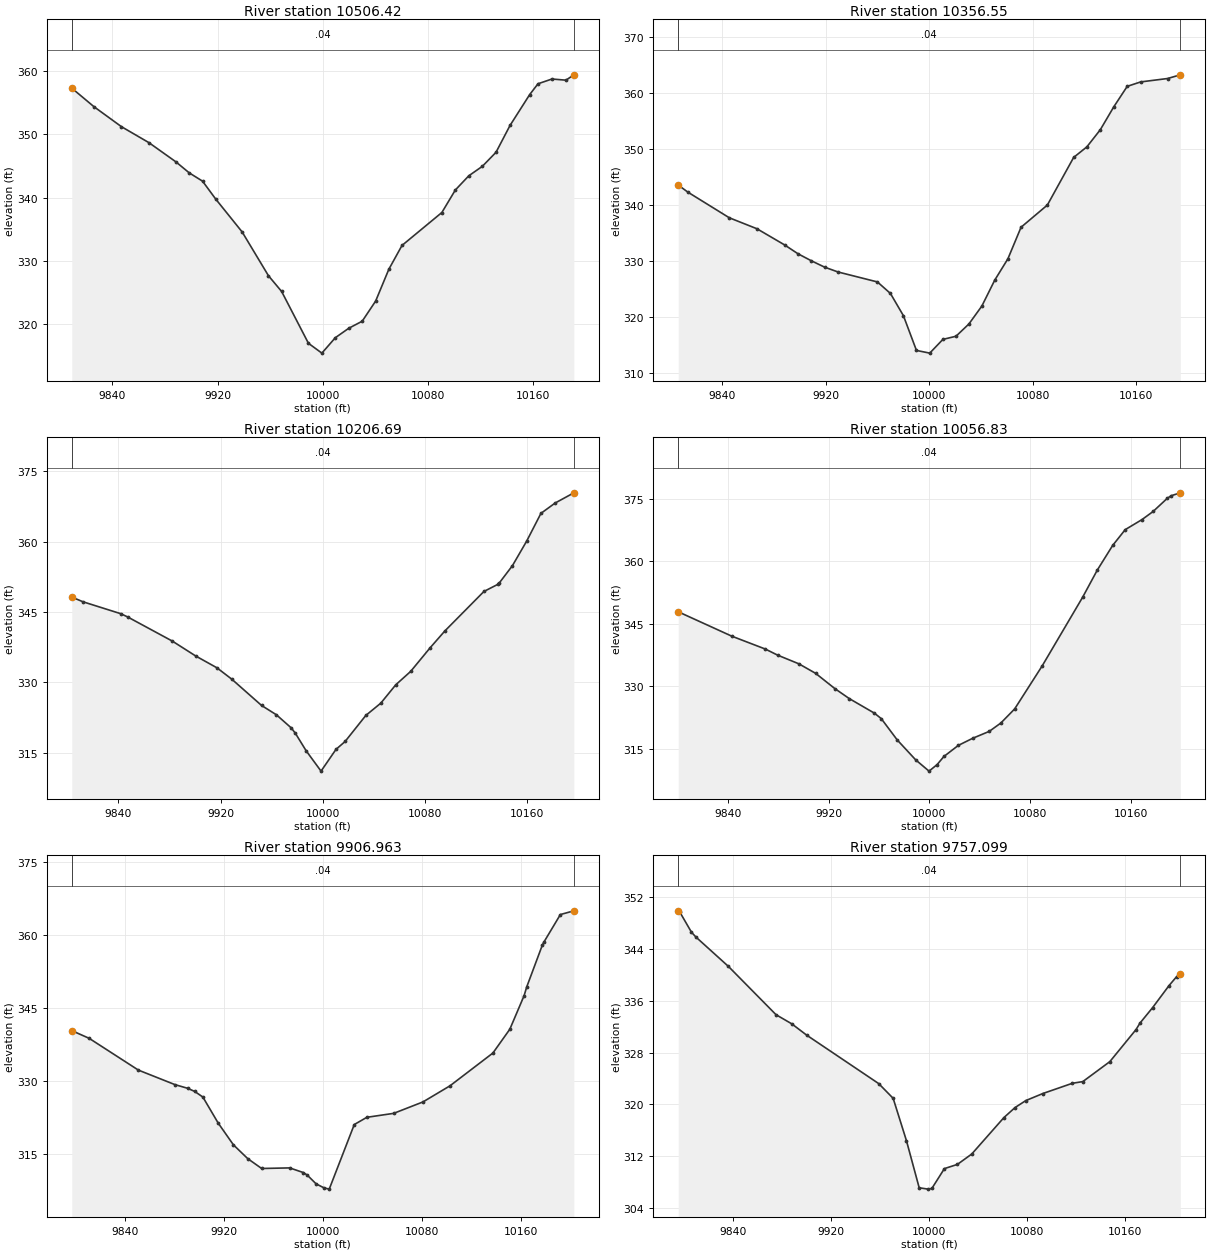
Type RM Length L Ch R = 1 ,10506.42,149.863900,149.863900,149.863900
XS GIS Cut Line= 6
815503.060412341785141.191150346815521.771548149785078.878092379
815530.143609626785019.740264496815513.604468165784913.730000119
815514.201657486784875.381083338815546.486456501784769.369313915
#Sta/Elev= 30
 9809.05357.27969825.955354.34359846.837351.19349867.719348.67119888.233345.6422
9898.408343.89619908.529342.58779918.573339.75039938.648334.56599958.676327.6476
 9968.69325.16359989.071316.98159999.289315.428810009.52317.863210019.74319.3562
10029.97320.470210040.19323.650810050.23328.675210060.24332.436710090.56337.6376
10100.82341.193710111.07343.440410121.33 344.92710131.76 347.152 10142.4351.3846
10157.33356.249910163.68357.968210174.32358.721110184.96358.535710190.95359.3812
#Mann= 3 , 0 , 0
 9809.05    0.04       0 9809.05    0.04       010190.95    0.04       0
#XS Ineff= 2 , 0
       0                               0
Bank Sta=9809.05,10190.95
Exp/Cntr=0.3,0.1

Type RM Length L Ch R = 1 ,10356.55,149.864000,149.864000,149.864000
XS GIS Cut Line= 6
815619.619021515785151.904905197815662.031576048785024.891675248
815664.963945733784991.032736562 815657.70510851784947.492209893
815659.034227376784912.774049746815691.643069144 784775.53210892
#Sta/Elev= 30
9805.878343.5744 9813.27342.31249845.388337.71089866.799335.7442 9888.07332.8634
9898.425331.2774 9908.78330.01629919.135328.8664 9929.49328.00589959.923326.2245
 9969.96324.16659980.003320.18399990.084313.965310000.36313.480210010.53315.9393
10020.65316.502410030.65318.700910040.66321.909410050.67326.5675 10060.8330.3702
10070.97336.019110091.31339.992210111.65348.521410121.85350.409610132.26353.4804
10142.66357.573410153.06361.244310163.47  362.0410184.27362.649110194.12363.3096
#Mann= 3 , 0 , 0
9805.878    0.04       09805.878    0.04       010194.12    0.04       0
#XS Ineff= 2 , 0
       0                               0
Bank Sta=9805.878,10194.12
Exp/Cntr=0.3,0.1

Type RM Length L Ch R = 1 ,10206.69,149.863900,149.863900,149.863900
XS GIS Cut Line= 6
815685.288730957785182.539911912815785.457836229785014.675066009
 815786.46282026 785012.94590231 815829.53858416784941.964055035
815850.590329034784903.203969858815880.781724792 784841.89767615
#Sta/Elev= 30
 9803.52348.1773  9812.3347.16829841.986344.61669847.235343.93679882.171338.7907
9900.532335.60469917.106333.09039928.751330.66139952.041325.05749963.686323.0602
9975.331320.25589978.592319.09259986.977315.37749998.622311.043310010.29315.6747
10017.46317.368410033.69322.930210045.39325.543110057.08329.452410068.78332.3213
10084.03337.367210095.47340.928810126.09349.368110137.28350.927410138.12351.1836
10148.43354.882210159.58360.123710170.72366.029210181.87368.240810196.48370.4126
#Mann= 3 , 0 , 0
 9803.52    0.04       0 9803.52    0.04       010196.48    0.04       0
#XS Ineff= 2 , 0
       0                               0
Bank Sta=9803.52,10196.48
Exp/Cntr=0.3,0.1

Type RM Length L Ch R = 1 ,10056.83,149.863900,149.863900,149.863900
XS GIS Cut Line= 6
815782.939079848785246.929642448815874.726949533  785142.5745817
815915.797779415785088.477198458815934.061644799785055.529838602
815969.095792312784976.315303277815998.142018263784915.531235351
#Sta/Elev= 30
9800.707347.8992 9843.23342.04879869.866338.95819879.534337.51039896.502335.4144
 9909.82333.12699924.958329.49379936.455327.08599956.475323.58049961.905 322.268
9974.548317.16449989.161312.39629999.797309.681610006.18311.2353 10011.6313.1917
10023.04 315.85210034.47317.559910047.62319.218410056.81321.219710067.75 324.591
10089.61334.911310121.79351.416710133.37357.897710145.61363.825510155.54367.6007
 10168.8370.0003 10177.7371.959910188.79375.073710191.99 375.73410199.28376.4306
#Mann= 3 , 0 , 0
9800.707    0.04       09800.707    0.04       010199.28    0.04       0
#XS Ineff= 2 , 0
       0                               0
Bank Sta=9800.707,10199.28
Exp/Cntr=0.3,0.1

Type RM Length L Ch R = 1 ,9906.963,149.864000,149.864000,149.864000
XS GIS Cut Line= 6
815874.417127902785239.785903292815998.077503718785142.977670085
816027.807733506785129.240556869 816072.54777633785133.380813058
816108.709347224785116.519870141816202.428321915785027.182476914
#Sta/Elev= 30
9797.124340.43839811.159338.85869850.946332.32559880.531329.33729890.667328.5931
9896.431327.94539903.058326.78629915.449321.43479927.755316.96119939.369314.1187
 9950.58312.10319973.199312.22559984.214311.26969987.307310.76819994.586308.9419
   10001308.118610005.17307.8629 10025.4321.136110035.58 322.62510057.26323.4354
10080.91325.783410102.73 329.09210137.43 335.83310151.11340.729210162.62347.6135
10164.78349.433710177.28357.947810178.46358.559110191.94364.291510202.83 365.058
#Mann= 3 , 0 , 0
9797.124    0.04       09797.124    0.04       010202.83    0.04       0
#XS Ineff= 2 , 0
       0                               0
Bank Sta=9797.124,10202.83
Exp/Cntr=0.3,0.1

Type RM Length L Ch R = 1 ,9757.099,149.863900,149.863900,149.863900
XS GIS Cut Line= 6
815924.084861933785382.070242966816042.192714862785282.048776754
816056.786784317785258.038457896816069.795942463 785211.99577651
816083.226508786785192.378736881816201.814478828785092.975197154
#Sta/Elev= 30
9795.168349.89149796.381349.72369805.945346.59379809.631345.83579836.131341.3014
9874.941333.84969887.755332.44259899.865330.70249958.724323.20599970.508320.9314
9981.382 314.3719991.743307.1156    9999306.908210002.06307.009910012.31310.0768
10022.94310.729210034.62312.329610060.88317.962910069.97319.511110078.76320.5877
10092.62321.673510116.73323.257210125.23323.516710147.29326.601210168.65331.5544
10171.89332.557510182.12334.928710195.59338.351210201.74339.722210204.77340.1887
#Mann= 3 , 0 , 0
9795.168    0.04       09795.168    0.04       010204.77    0.04       0
#XS Ineff= 2 , 0
       0                               0
Bank Sta=9795.168,10204.77
Exp/Cntr=0.3,0.1

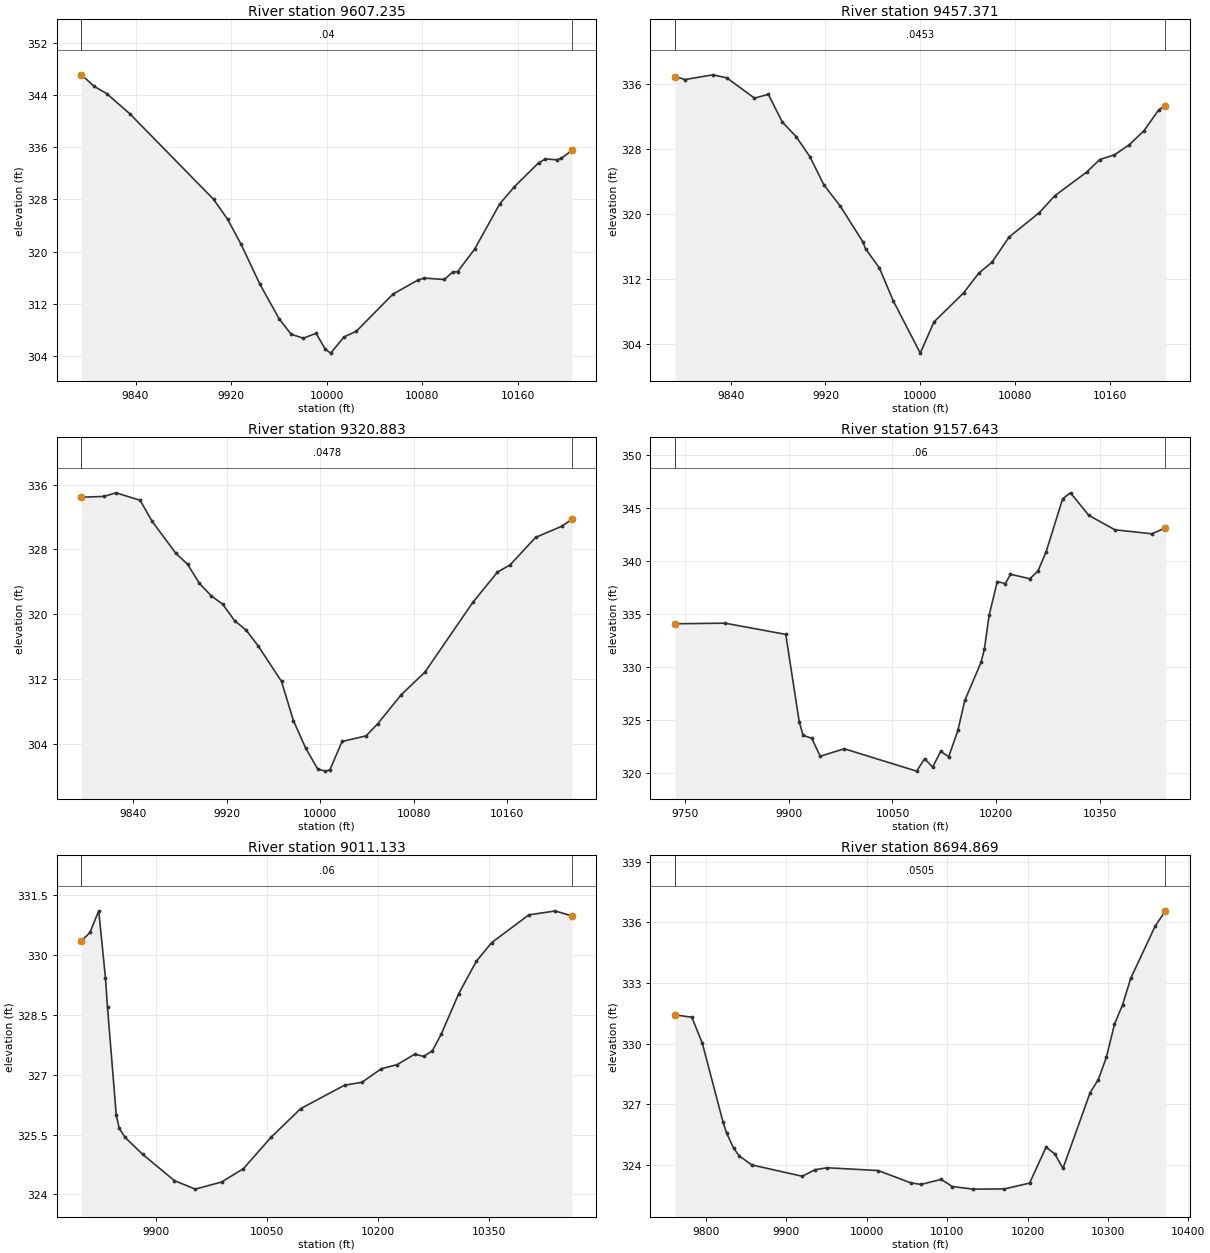
Type RM Length L Ch R = 1 ,9607.235,149.863900,149.863900,149.863900
XS GIS Cut Line= 6
815929.330032949785412.276169356816042.290268874785327.262757189
816077.124256636785320.274141874816153.083482535785334.664862996
816217.583842215785306.688079217816281.476782907785256.499036451
#Sta/Elev= 30
9794.708347.14649805.522345.35969815.891344.26529835.383341.13529905.301328.0338
9917.019324.98389928.354321.13759944.001315.03729960.276309.66969970.295307.3025
 9980.55   306.7 9991.19307.4397    9999304.975510003.43304.401810014.55306.8846
10024.86307.758610055.49313.455410076.78315.660810081.74315.924610098.57315.7147
 10105.5316.851210109.78316.933610123.89  320.3610144.99327.336510157.11329.9347
10177.46333.624210183.25334.226610192.51334.100310196.63334.3401 10205.3335.5306
#Mann= 3 , 0 , 0
9794.708    0.04       09794.708    0.04       0 10205.3    0.04       0
#XS Ineff= 2 , 0
       0                               0
Bank Sta=9794.708,10205.3
Exp/Cntr=0.3,0.1

Type RM Length L Ch R = 1 ,9457.371,136.488200,136.488200,136.488200
XS GIS Cut Line= 6
 816092.25623801785602.269021041  816190.1211472785442.173345183
816199.630400398785424.108412788816208.383127364785409.346749138
 816284.74718913785314.089054829816324.542554848785260.468430968
#Sta/Elev= 30
9792.933336.93139801.452336.56489824.893337.13959836.613336.77259860.054334.2764
9871.775334.74149883.495331.33929895.215329.54649906.936327.04749918.656323.6031
9932.406 321.0179951.579316.60249953.817315.74559965.538313.39049977.258309.3382
10000.04302.919410011.59306.752510036.55310.310910049.37312.739810060.72314.1204
   10075317.185310100.63320.204610113.45 322.24910140.67325.191210151.57326.7198
10164.02327.304210176.47328.535710188.93330.263210201.38332.827710207.02333.3488
#Mann= 3 , 0 , 0
9792.933  0.0453       09792.933  0.0453       010207.02  0.0453       0
#XS Ineff= 2 , 0
       0                               0
Bank Sta=9792.933,10207.02
Exp/Cntr=0.3,0.1

Type RM Length L Ch R = 1 ,9320.883,163.239700,163.239700,163.239700
XS GIS Cut Line= 6
816307.422893731 785673.42859838816330.476789949 785548.37489144
816309.247736232785437.552195219816308.704757251785396.589266572
816323.894441227785331.401347262816352.483285262 785267.07470769
#Sta/Elev= 30
9795.637334.44579814.792 334.5419825.187334.98689845.808334.06849856.042 331.491
9876.343327.53279886.445326.16629896.548323.81689906.571322.28779916.586321.2194
9926.598319.21949936.605 318.0259946.611316.13769966.789311.71189977.026306.8516
9987.396303.49669997.766300.888210004.41300.632210008.22300.797610018.56304.2907
10039.16 304.98610049.19306.499710069.22310.0657 10089.4312.841610130.51321.4735
10151.57 325.20510162.31326.088210184.18329.485310206.35330.850510215.13331.6993
#Mann= 3 , 0 , 0
9795.637  0.0478       09795.637  0.0478       010215.13  0.0478       0
#XS Ineff= 2 , 0
       0                               0
Bank Sta=9795.637,10215.13
Exp/Cntr=0.3,0.1

Type RM Length L Ch R = 1 ,9157.643,146.510400,146.510400,146.510400
XS GIS Cut Line= 4
 816316.02673164785672.632003799816440.657700449785508.879206285
 816552.81142965785320.398633644816703.746243656785078.395055339
#Sta/Elev= 30
9735.011334.06629807.436334.12149895.404333.06669914.943324.83749920.538323.5588
9933.105323.28239945.311321.5866 9980.22322.292110084.95320.186110096.58  321.35
10108.22320.567310119.86322.044810131.49321.545910144.85324.037110154.77326.8391
10178.27330.432710183.15331.670110190.06334.878510201.84338.045410213.63337.8481
10220.95338.729810248.98338.308510260.77339.029310272.55  340.8410296.53345.8392
10307.91 346.39810334.33344.281610372.12342.917510425.77342.540510445.34343.0905
#Mann= 3 , 0 , 0
9735.011    0.06       09735.011    0.06       010445.34    0.06       0
#XS Ineff= 2 , 0
       09940.012        10037.42       0
Bank Sta=9735.011,10445.34
Exp/Cntr=0.3,0.1

Type RM Length L Ch R = 1 ,9011.133,316.264100,316.264100,316.264100
XS GIS Cut Line= 2
816487.600410312785704.697138682816843.069160283785146.103388682
#Sta/Elev= 29
9799.873330.34859811.367330.5614 9823.22331.10439832.282329.43299835.073328.6836
9846.927325.97869850.908325.6602 9858.78325.42759882.486 325.0059925.414324.3446
9953.604324.13179989.164324.310410018.55324.6441 10055.8325.428510095.84326.1476
10155.11326.735310178.81326.810410204.81327.148410226.23327.250910249.93327.5139
10261.78327.456610273.64327.596910285.49328.0079 10309.2329.0248 10332.9329.8362
10353.82330.308310404.02331.003610439.58331.100710461.98330.9778
#Mann= 3 , 0 , 0
9799.873    0.06       09799.873    0.06       010461.98    0.06       0
#XS Ineff= 2 , 0
       09941.276        10043.33       0
Bank Sta=9799.873,10461.98
Exp/Cntr=0.3,0.1

Type RM Length L Ch R = 1 ,8694.869,63.751500,63.751500,63.751500
XS GIS Cut Line= 3
816678.860972627785855.832895267   817051.256806 785548.54122861
817034.329722627785422.239145282
#Sta/Elev= 30
9761.319331.42439782.244331.30579795.209330.03169821.139326.10589825.475325.5765
9834.104324.83689841.187324.44139856.899323.99459919.746323.43279935.458323.7566
9950.789323.853510014.02323.716710054.51323.109510067.47 323.02910092.58323.2779
10106.37322.9249 10132.3322.795610171.14322.806110202.56323.093610223.05324.8706
10233.98324.539910244.13323.825710277.97327.577210288.06328.215110298.15329.3263
10308.24330.960510318.33331.929710328.42333.231510358.69335.805810371.56336.5758
#Mann= 3 , 0 , 0
9761.319  0.0505       09761.319  0.0505       010371.56  0.0505       0
#XS Ineff= 2 , 0
       09940.824        10059.79       0
Bank Sta=9761.319,10371.56
Exp/Cntr=0.3,0.1

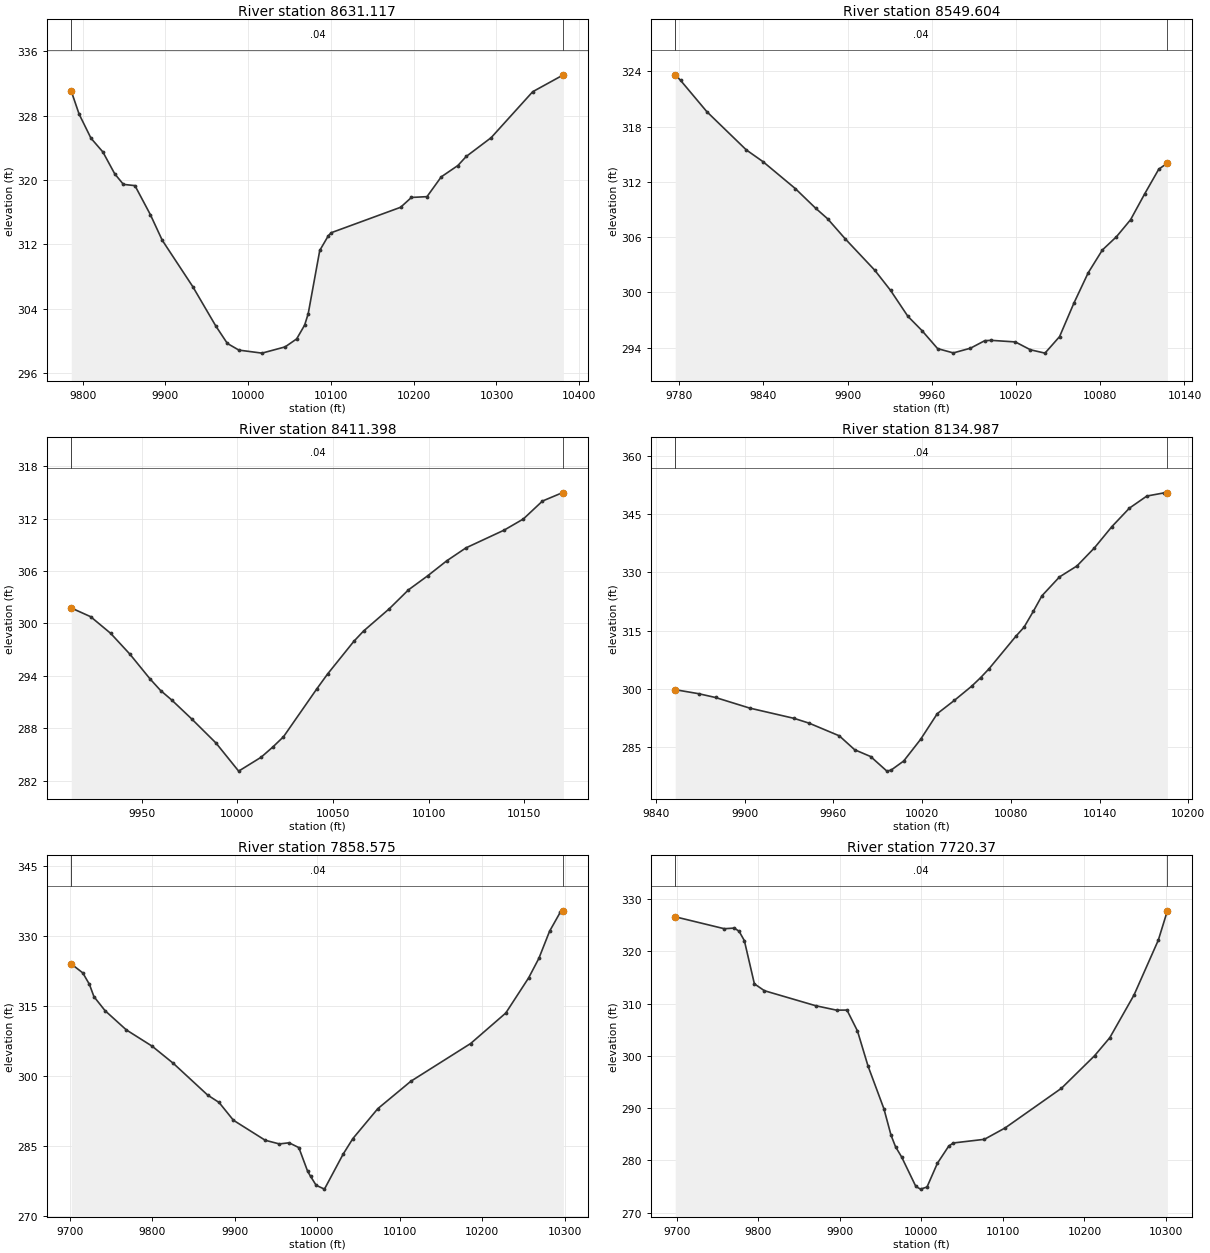
Type RM Length L Ch R = 1 ,8631.117,81.513100,81.513100,81.513100
XS GIS Cut Line= 3
816768.376925439785890.131712765 817068.11104548785582.148029804
 817052.52853775785418.073389158
#Sta/Elev= 30
9786.318331.05939795.814328.19689810.152325.2019 9824.49323.49789838.828320.7764
9849.295319.46529863.249319.30949881.843315.70749896.181312.52369933.019306.7621
9960.927301.85119974.881299.68059988.835298.851810016.74298.476210044.65299.2507
10058.61300.244310068.24301.959210072.56 303.37810086.51311.248610096.91313.0822
10100.47 313.45610184.19 316.61610197.28317.839810216.08317.9386 10233.3320.4017
10253.39321.810110263.44322.934710293.57325.2728 10343.8330.991810380.89 333.091
#Mann= 3 , 0 , 0
9786.318    0.04       09786.318    0.04       010380.89    0.04       0
#XS Ineff= 2 , 0
       09942.241        10059.46       0
Bank Sta=9786.318,10380.89
Exp/Cntr=0.3,0.1

Type RM Length L Ch R = 1 ,8549.604,138.205700,138.205700,138.205700
XS GIS Cut Line= 6
816882.938085643785967.803756111816940.871486854785872.054696335
816991.541980057785770.950089021817001.746107141785746.524150485
817008.774341617785721.237481439 817017.31452444785648.882442666
#Sta/Elev= 30
 9777.16323.62439781.017323.01289799.723319.61429827.808315.46829839.641314.2007
9862.687311.27379877.246309.1327 9885.71307.9947 9898.31305.80719919.367302.3973
9930.554300.21979942.923297.39869952.928295.85459964.115293.89039975.302293.4234
9987.536293.93679997.677294.750510002.19  294.7910019.48294.616410030.25 293.763
10040.62293.4005   10051295.193810061.24 298.83910071.38 302.11910081.51304.6039
10091.55306.044210101.59307.887810111.63310.692310121.67 313.37510127.82314.0396
#Mann= 3 , 0 , 0
 9777.16    0.04       0 9777.16    0.04       010127.82    0.04       0
#XS Ineff= 2 , 0
       0                               0
Bank Sta=9777.16,10127.82
Exp/Cntr=0.3,0.1

Type RM Length L Ch R = 1 ,8411.398,276.411400,276.411400,276.411400
XS GIS Cut Line= 6
817143.930836856785845.008260444817143.946341187785824.577864617
817137.554145545 785804.94415918817093.051763028785730.144071788
817079.314544588785697.391449973817077.071592361785604.054583266
#Sta/Elev= 27
9913.207301.76629923.327300.77149933.787298.8646 9943.86296.47789954.376293.6476
9959.899292.31999965.684291.23719976.125289.07159988.856286.306410000.69283.0905
10012.41284.677910018.55285.853410024.12287.023410041.51292.499610047.17294.2107
 10060.9297.951410065.96299.125410079.46301.688110089.46303.846310099.46305.4463
10109.47307.171710119.47308.645710139.48310.684910149.48311.954610159.48314.0096
10169.48314.927510170.43314.9507
#Mann= 3 , 0 , 0
9913.207    0.04       09913.207    0.04       010170.43    0.04       0
#XS Ineff= 2 , 0
       0                               0
Bank Sta=9913.207,10170.43
Exp/Cntr=0.3,0.1

Type RM Length L Ch R = 1 ,8134.987,276.411500,276.411500,276.411500
XS GIS Cut Line= 6
817193.399045974785822.748636574817216.733423859785803.044517294
817235.246156096785795.475200608 817285.90446496785790.205271959
817327.603780597785774.995392039817486.758673608785677.272874713
#Sta/Elev= 30
9852.939299.84329868.799298.81279880.177297.83689903.275295.11669933.456292.4602
 9943.51291.23739963.925287.98059974.316284.40389985.104282.66079996.129278.9062
9998.989279.177210007.48 281.50410018.86287.042310030.23293.6941 10041.8297.1052
10053.48 300.74610059.59302.968210065.17305.206710083.44313.613310088.87315.8984
10095.25320.041510101.02323.997410112.85328.828310124.67331.650810136.49336.2976
10148.32 341.77210160.14346.513210171.96349.629710183.79 350.45810185.86350.4376
#Mann= 3 , 0 , 0
9852.939    0.04       09852.939    0.04       010185.86    0.04       0
#XS Ineff= 2 , 0
       0                               0
Bank Sta=9852.939,10185.86
Exp/Cntr=0.3,0.1

Type RM Length L Ch R = 1 ,7858.575,138.205700,138.205700,138.205700
XS GIS Cut Line= 6
817100.271501991 786175.39384891817274.853982827785997.288768863
817307.041985551785922.761834907817444.102735684785899.950417486
817498.954885629785870.799400004817548.028106992 785833.30022269
#Sta/Elev= 30
9701.592324.0746  9715.6322.14789723.562319.71239729.077317.06969742.553314.0615
9768.312309.94439799.627 306.4519825.344302.76739867.012295.95949880.762  294.39
9898.192290.57519936.747286.28289953.877285.49679965.691285.74029977.504284.7105
9988.286279.59179991.718278.56569998.481 276.63710008.57275.807610031.16283.2845
10043.06 286.64910073.28293.055810113.37298.932810185.85307.021710228.46313.5576
10256.23321.111610268.63 325.29610281.54331.083410294.44335.132710298.34335.4609
#Mann= 3 , 0 , 0
9701.592    0.04       09701.592    0.04       010298.34    0.04       0
#XS Ineff= 2 , 0
       0                               0
Bank Sta=9701.592,10298.34
Exp/Cntr=0.3,0.1

Type RM Length L Ch R = 1 , 7720.37,138.205700,138.205700,138.205700
XS GIS Cut Line= 6
817159.513329762786303.962467655817242.034635526786188.400322013
817299.909388929786116.459712641817373.668785249786051.136272378
817450.031549215785958.503760922817561.013778068785857.496155893
#Sta/Elev= 30
9698.344326.59239758.509 324.3119770.796324.43489776.617  323.829783.084 322.032
9795.372313.7638 9807.66312.45099870.378309.58439896.047308.7301 9908.89308.7442
9921.715 304.7559934.728298.01379954.146289.86119962.845284.81829968.373282.6026
9975.822280.64839993.273275.0051    9999274.485710006.99274.891410019.71279.4326
10033.59282.715910039.23283.318310077.33 284.01710102.73286.1933 10171.8293.7859
10212.36300.006410231.05303.462210260.76311.636810290.48322.110810301.63327.7352
#Mann= 3 , 0 , 0
9698.344    0.04       09698.344    0.04       010301.63    0.04       0
#XS Ineff= 2 , 0
       0                               0
Bank Sta=9698.344,10301.63
Exp/Cntr=0.3,0.1

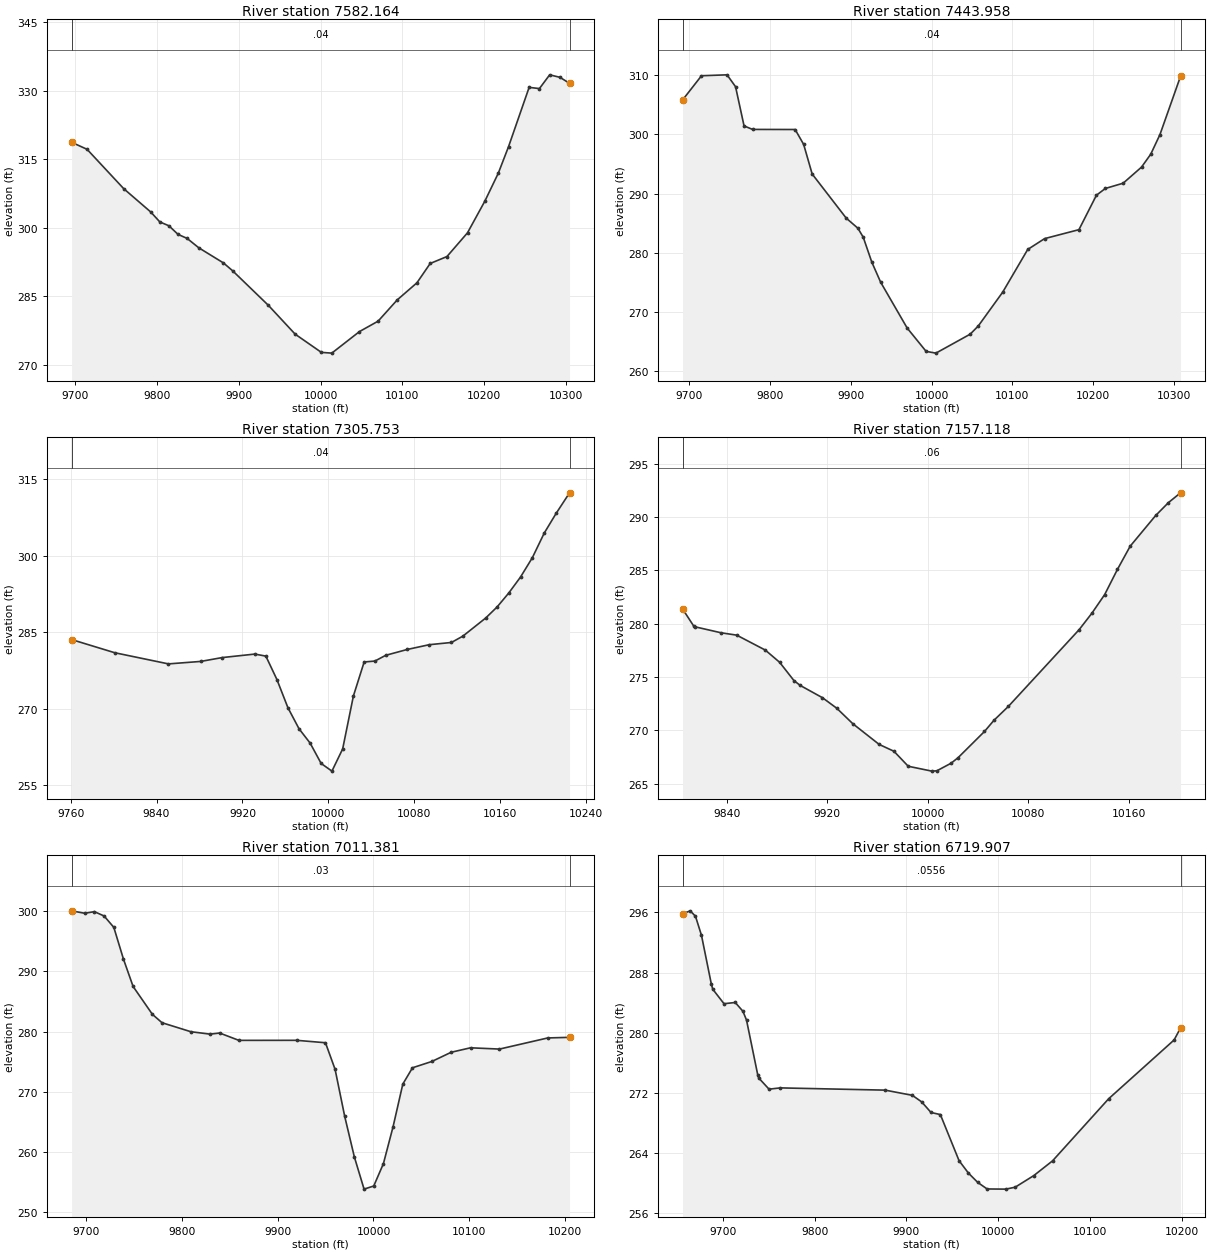
Type RM Length L Ch R = 1 ,7582.164,138.205700,138.205700,138.205700
XS GIS Cut Line= 6
817347.225634652786342.067996862817434.243328056786162.467688972
817467.598893699786086.504060214 817506.22259477786011.780870994
817551.708969287785941.879726987817647.496940518 785815.65350251
#Sta/Elev= 30
  9695.7318.71459714.666317.17299759.399308.57049792.449303.46969803.561301.2936
9814.673300.44859825.785298.57329836.897297.69029851.137295.63999881.344292.3201
9892.456290.61869936.191283.05429968.955276.7441   10001272.759110013.75 272.596
10047.52 277.30810070.34279.589110093.74284.248510117.78287.977210133.98 292.204
10154.47 293.72110179.57298.9118 10200.9 305.87910217.23311.957310229.79 317.785
10254.89330.722810267.45 330.459   10280333.466210292.55332.920910304.29 331.606
#Mann= 3 , 0 , 0
  9695.7    0.04       0  9695.7    0.04       010304.29    0.04       0
#XS Ineff= 2 , 0
       0                               0
Bank Sta=9695.7,10304.29
Exp/Cntr=0.3,0.1

Type RM Length L Ch R = 1 ,7443.958,138.205700,138.205700,138.205700
XS GIS Cut Line= 6
817447.244694596786467.277800009817520.181591163786245.552116884
817565.047307454786160.746457844 817572.70240973 786090.13455432
817593.433436928786020.069274472817655.324122822785892.701515415
#Sta/Elev= 30
9692.102305.79489715.554309.89369747.135310.04859757.662308.04499768.189301.4229
9778.717300.83529831.352300.81999841.879298.30539852.407293.30879894.515 285.861
9908.933284.1588 9915.57282.63199926.119278.44289937.048 275.0559969.835267.3171
9993.321263.370410005.41263.078210047.77266.275810057.78267.658810088.02273.3755
10118.92280.574110139.78 282.40410182.26283.916710203.88289.7284 10214.9290.8695
10236.92291.756410259.64294.473110271.04296.652910282.44299.969810307.85309.7906
#Mann= 3 , 0 , 0
9692.102    0.04       09692.102    0.04       010307.85    0.04       0
#XS Ineff= 2 , 0
       0                               0
Bank Sta=9692.102,10307.85
Exp/Cntr=0.3,0.1

Type RM Length L Ch R = 1 ,7305.753,148.634700,148.634700,148.634700
XS GIS Cut Line= 6
817655.082017243786355.113562539817660.955050468786197.194224924
817644.001324978786128.697020342817646.094387755786053.828168287
817656.173542346786006.239331257817698.785619474785903.600238821
#Sta/Elev= 30
9760.916283.56579801.057280.98249851.092278.78829881.112279.27239901.126280.0297
9931.478280.71619941.756280.31479952.035275.72099962.313270.16899972.601266.0598
9982.977263.22999993.217259.241410003.24257.735710013.24262.096210023.24272.4965
10033.24279.163510043.25279.345610053.28280.472110073.42281.624410093.83282.5577
10114.48282.9946 10125.1284.236310146.33287.788510156.95289.958910167.84292.7058
10178.78295.8403 10189.8299.643710200.83304.465210211.85308.317410224.41312.3732
#Mann= 3 , 0 , 0
9760.916    0.04       09760.916    0.04       010224.41    0.04       0
#XS Ineff= 2 , 0
       0                               0
Bank Sta=9760.916,10224.41
Exp/Cntr=0.3,0.1

Type RM Length L Ch R = 1 ,7157.118,145.736900,145.736900,145.736900
XS GIS Cut Line= 3
817690.320216537786332.926548153817839.103724688786058.851664692
817853.959403181785975.569830675
#Sta/Elev= 30
9804.857281.38299813.876279.75299814.666279.70559835.626279.14029848.011278.9201
9870.768277.51919882.147276.37769893.525274.66719898.507274.20929916.282273.0547
9927.661272.06729940.428270.61759961.388268.67839973.175 268.0359984.553266.6302
10003.31266.174110007.31266.203810018.69266.917210024.27267.437910045.23269.8892
10052.82 270.942 10064.2272.232910120.62279.436910130.78280.980610140.94282.7239
 10151.1285.085210161.26287.262310181.57290.140310191.73 291.34710201.31292.2611
#Mann= 3 , 0 , 0
9804.857    0.06       09804.857    0.06       010201.31    0.06       0
#XS Ineff= 2 , 0
       0                               0
Bank Sta=9804.857,10201.31
Exp/Cntr=0.3,0.1

Type RM Length L Ch R = 1 ,7011.381,291.473900,291.473900,291.473900
XS GIS Cut Line= 6
817886.715982145786528.580164958817898.423216861786437.403174343
817907.911556033786301.333312528817913.814074636786241.190851304
817926.867303721786149.702256222817943.851592849786012.465878691
#Sta/Elev= 30
9685.071 300.0859698.806299.6806 9708.92299.94789719.033299.22299729.147297.3334
9739.211292.05449749.267287.5061 9769.38282.87719779.428281.47959809.501279.9858
 9829.55279.58149839.574279.76689859.623278.54689919.783278.55489949.928278.1525
9959.976 273.7269970.024265.89269980.101259.14449990.196253.8128 10000.3254.3347
 10010.4258.0599 10020.5264.217910030.61271.275510040.71  273.9910060.91 275.038
10081.08276.569610101.23277.310910131.46277.098410181.84278.950310204.55279.0491
#Mann= 3 , 0 , 0
9685.071    0.03       09685.071    0.03       010204.55    0.03       0
#XS Ineff= 2 , 0
       0                               0
Bank Sta=9685.071,10204.55
Exp/Cntr=0.3,0.1

Type RM Length L Ch R = 1 ,6719.907,122.064600,122.064600,122.064600
XS GIS Cut Line= 3
818066.801374243786411.825513757818202.545224951786221.259582958
818142.756235378785918.118916533
#Sta/Elev= 30
9655.863295.80829664.243296.21369669.994  295.499676.521292.9587 9687.23286.5084
9688.798285.79889701.076283.87099713.353 284.0349721.702282.86679725.631281.6952
9737.909274.39259738.939274.00069750.186272.51499762.464272.68529876.827 272.386
9906.405271.69669916.598270.82579926.791269.41639936.983269.13869957.369263.0114
9967.561261.36589977.754260.12149987.946 259.25410008.33259.232510018.52259.4875
10038.91261.0366 10059.3262.990610120.45271.2398 10191.8 279.05110198.81280.6401
#Mann= 3 , 0 , 0
9655.863  0.0556       09655.863  0.0556       010198.81  0.0556       0
#XS Ineff= 2 , 0
       0                               0
Bank Sta=9655.863,10198.81
Exp/Cntr=0.3,0.1