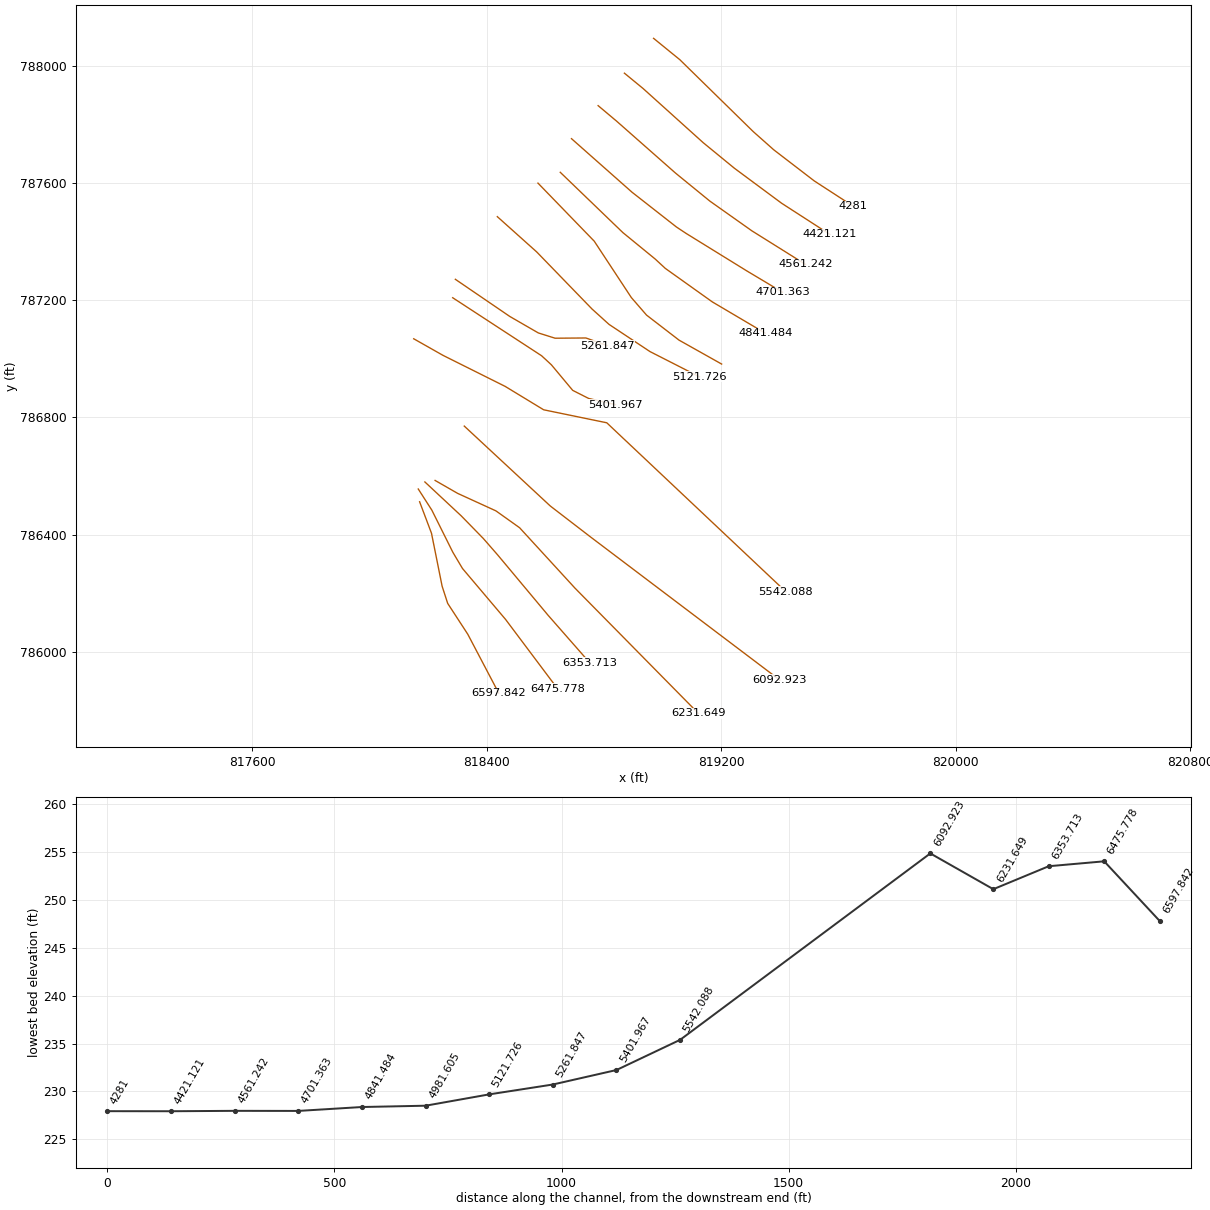
HEC-RAS study 17400_ras.prj: 17400

--- 17400_ras.g01 (geometry) --- (continued)

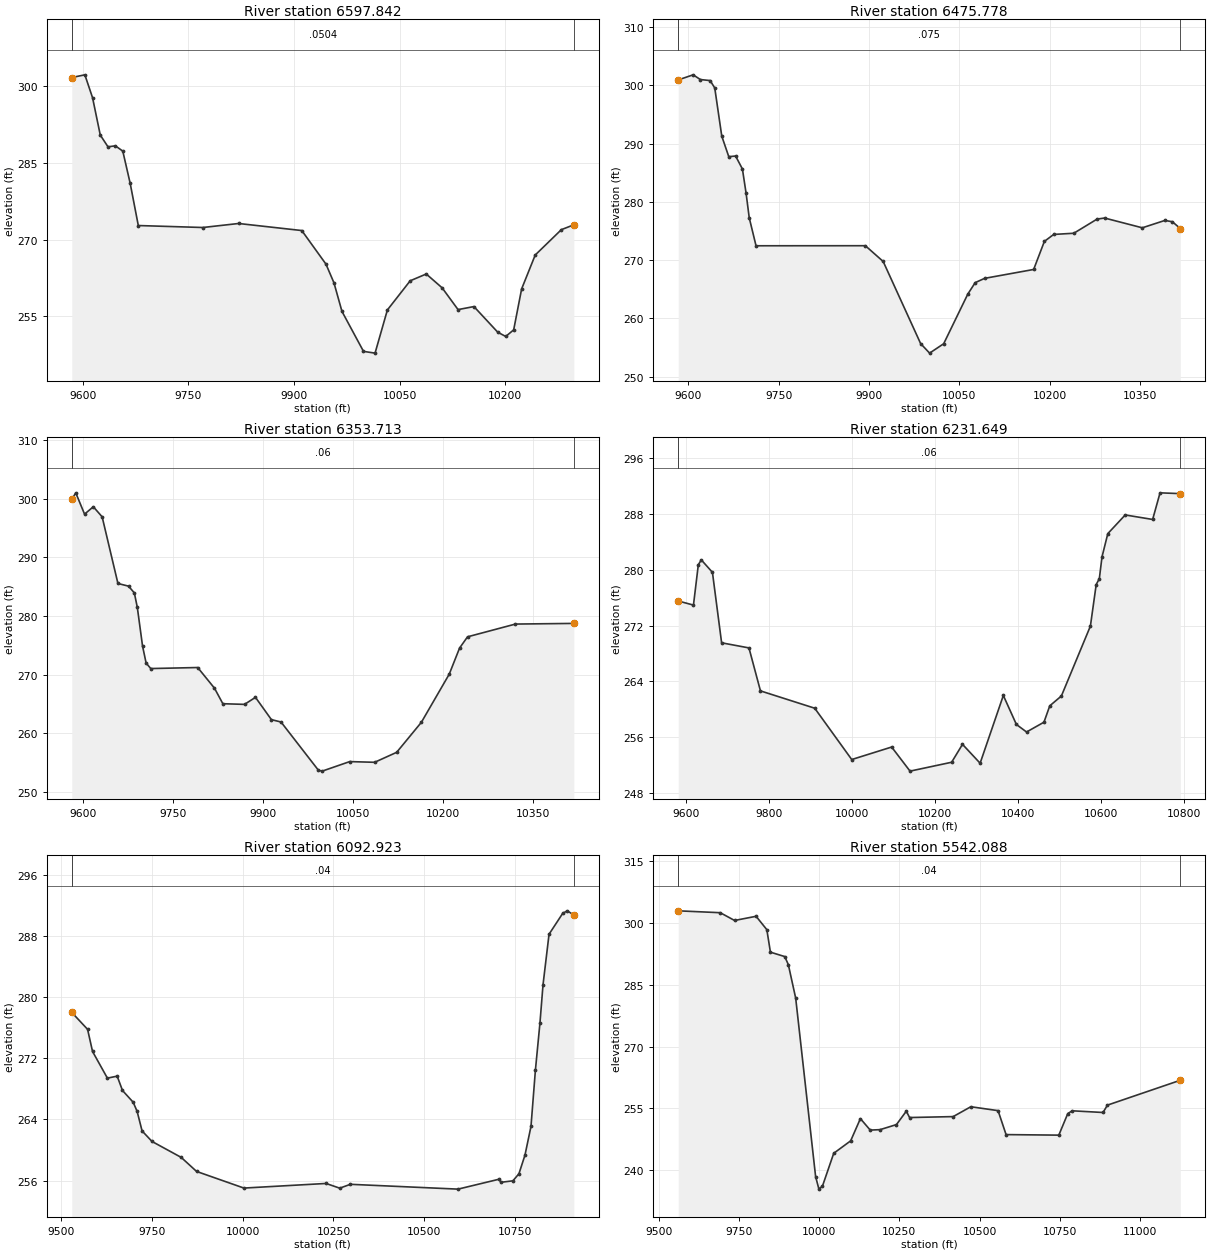
Type RM Length L Ch R = 1 ,6597.842,122.064600,122.064600,122.064600
XS GIS Cut Line= 6
818170.741468834786511.993908447818211.269388181786404.542461668
818247.535236489786223.921425499818266.497086139 786165.31924071
818335.053578441786060.083601155818440.607517351785859.340057486
#Sta/Elev= 30
9584.172 301.7469602.784302.27279613.736 297.7829624.688290.48529635.639288.1892
9646.169288.37719656.675287.34789667.181281.04269678.733 272.7839770.409272.3987
9821.288273.18329911.088271.80269945.466  265.239956.824261.57229968.182255.9814
9998.783248.161710015.21247.818110032.74256.266810065.16261.972810087.98263.3024
10110.57 260.59110133.16256.334810155.75256.928610189.64251.904810200.94251.0814
10212.23252.372110223.53260.381810242.85 267.01810280.01271.979110297.74272.9255
#Mann= 3 , 0 , 0
9584.172  0.0504       09584.172  0.0504       010297.74  0.0504       0
#XS Ineff= 2 , 0
       0                10075.93       0
Bank Sta=9584.172,10297.74
Exp/Cntr=0.3,0.1

Type RM Length L Ch R = 1 ,6475.778,122.064700,122.064700,122.064700
XS GIS Cut Line= 6
818166.104040793786555.528665802818212.554875457786483.231031804
818284.210872156 786339.53060786818316.959595554786284.385465231
818464.021849397786110.568057177818641.135933779785874.482978361
#Sta/Elev= 30
9583.218300.91759607.962301.78889620.015300.97749636.193300.80519643.848299.5376
9655.486291.27759667.124287.74859678.483287.85839689.783285.6345 9695.91281.4596
9701.083277.27689712.383272.46299893.915272.47329923.498269.77019985.681255.6845
10000.58254.046510023.96255.658610063.98264.167410076.26266.138410091.92266.8744
10173.34268.399110191.18 273.22210206.66274.409310239.99274.610310278.69277.0428
10291.19277.2213 10353.7275.5461 10391.2276.8085 10403.7276.584410416.85275.4209
#Mann= 3 , 0 , 0
9583.218   0.075       09583.218   0.075       010416.85   0.075       0
#XS Ineff= 2 , 0
       0                               0
Bank Sta=9583.218,10416.85
Exp/Cntr=0.3,0.1

Type RM Length L Ch R = 1 ,6353.713,122.064600,122.064600,122.064600
XS GIS Cut Line= 6
 818188.73227729786579.533932946818312.745318125786463.838466551
818388.139854085786386.613878976818437.220332246786330.385719385
818608.897329971786124.906717358818751.973214988785961.810201828
#Sta/Elev= 30
9581.569299.89189588.216301.02599602.875297.38749617.493298.64849632.194296.9303
9658.521285.55539676.171285.10069685.874283.94579690.831281.4756 9699.55274.8757
 9705.49271.98039713.226271.03779791.474271.21369819.425267.69099833.401265.0383
9869.529264.92519887.786266.12559914.334262.31969930.356261.91899992.692253.6854
    9999253.534210044.86255.160310086.38255.041310123.12256.742310164.27 261.862
10210.75 270.08110227.97274.535810241.27276.454110321.09278.630910418.45 278.742
#Mann= 3 , 0 , 0
9581.569    0.06       09581.569    0.06       010418.45    0.06       0
#XS Ineff= 2 , 0
       0                10096.43       0
Bank Sta=9581.569,10418.45
Exp/Cntr=0.3,0.1

Type RM Length L Ch R = 1 ,6231.649,138.725400,138.725400,138.725400
XS GIS Cut Line= 6
818223.629203051786584.692385033 818300.49791497786540.584682375
818431.145693302786480.861142144 818511.81258446786423.390089005
818701.245562971786216.835576922819121.705888122785790.080722094
#Sta/Elev= 30
9580.493275.54259617.233274.95429628.944280.7464 9636.18281.43729662.984279.6523
9685.115269.54269751.087268.81019778.813262.64529909.684260.1595    9999252.7957
10095.28  254.5910139.61251.132710239.97252.406110266.17254.977310308.68252.2677
10364.68261.9867 10396.2257.826510420.68256.747110462.68258.152410476.68260.5005
10504.69261.909410574.69 271.93810588.69277.902310596.24278.745110602.69281.8674
10616.69285.206910658.69287.886210724.84287.238910742.69291.059610791.57290.9424
#Mann= 3 , 0 , 0
9580.493    0.06       09580.493    0.06       010791.57    0.06       0
#XS Ineff= 2 , 0
       0                10105.38       0
Bank Sta=9580.493,10791.57
Exp/Cntr=0.3,0.1

Type RM Length L Ch R = 1 ,6092.923,550.834800,550.834800,550.834800
XS GIS Cut Line= 4
818323.094777048786770.115444347818616.497554809 786497.54599987
818751.914221466786393.379333198819399.483665943785903.795999885
#Sta/Elev= 30
9529.006277.99079572.554275.77749586.204272.88199627.152269.39219654.062 269.653
9668.755267.7756 9698.14266.24269709.047265.04389722.697262.48859749.995261.1106
9830.373259.02729872.839 257.18710003.29255.011410229.56255.614210267.17254.9991
10296.62255.503210593.11 254.87310705.94256.166910711.16255.763410744.32255.9608
10760.91256.888910777.49259.319610794.07263.076110806.23270.424310818.76276.5907
10827.23281.608410843.81288.216810881.44 290.94610893.98291.278410912.14290.7294
#Mann= 3 , 0 , 0
9529.006    0.04       09529.006    0.04       010912.14    0.04       0
#XS Ineff= 2 , 0
       0                10125.91       0
Bank Sta=9529.006,10912.14
Exp/Cntr=0.3,0.1

Type RM Length L Ch R = 1 ,5542.088,140.120900,140.120900,140.120900
XS GIS Cut Line= 6
818150.586544904787068.025186046 818250.34715448787011.521306356
818462.575504479786905.572494881818593.928708161786825.727995214
818809.205888122786781.400166556819420.316999257786205.011277661
#Sta/Elev= 30
9560.281302.95639691.309302.50049736.016300.61459803.078301.62899836.608 298.383
9847.785292.92179892.492291.84849903.669289.89139926.599281.75289988.699 238.452
    9999235.390110010.15236.139410045.25244.0938   10098247.1109 10128.4252.5081
10159.08249.721510189.76249.830310240.89251.061610271.56254.313410281.79252.7708
10417.77252.999510472.76255.390210557.76254.445410582.73248.628610747.22248.4977
10775.17 253.73210788.92254.406710885.14253.995610898.89255.783611126.14261.8206
#Mann= 3 , 0 , 0
9560.281    0.04       09560.281    0.04       011126.14    0.04       0
#XS Ineff= 2 , 0
       0                10111.08       0
Bank Sta=9560.281,11126.14
Exp/Cntr=0.3,0.1

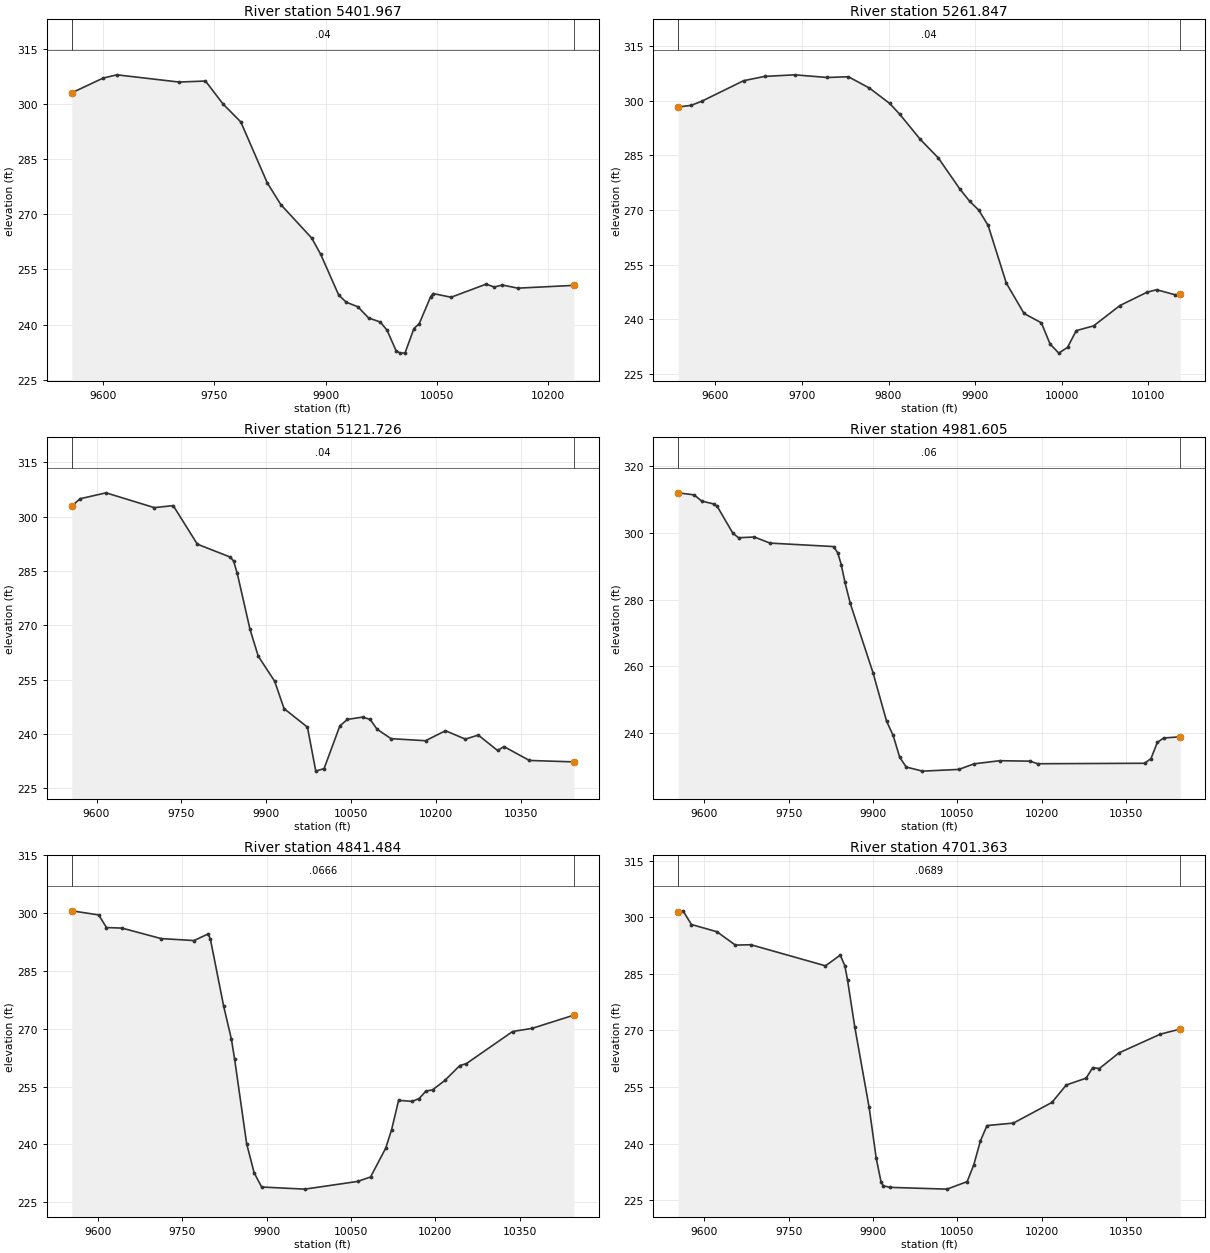
Type RM Length L Ch R = 1 ,5401.967,140.120900,140.120900,140.120900
XS GIS Cut Line= 6
818283.576322816787208.028385867818587.012708811787009.966773378
818620.217250719786979.238477176 818693.06024533786891.962381474
818747.226762182786864.505438821818838.766671262786843.265082047
#Sta/Elev= 30
9557.856302.98089600.279306.9963  9618.7307.87049702.436 305.9099738.157306.1854
9761.971299.91479785.786295.06319821.507 278.4969839.761272.59979881.343 263.518
9893.491259.09929917.788248.02299927.974246.07269943.558244.84519957.996241.8119
 9973.86240.68639982.948238.48179995.172232.8874   10001232.2345 10007.2 232.268
10019.21238.904510026.39240.249710041.81247.598510045.24248.425710069.31 247.421
 10116.6250.987210127.48250.197810138.37250.741510159.36249.894210234.86250.6503
#Mann= 3 , 0 , 0
9557.856    0.04       09557.856    0.04       010234.86    0.04       0
#XS Ineff= 2 , 0
       0                               0
Bank Sta=9557.856,10234.86
Exp/Cntr=0.3,0.1

Type RM Length L Ch R = 1 ,5261.847,140.121000,140.121000,140.121000
XS GIS Cut Line= 6
818292.624655364787270.876191392818478.409997478787144.118497269
818575.689256345 787087.89410463818632.870075995787069.906798672
818738.135714217787070.709223571818810.415328136787044.851634346
#Sta/Elev= 30
9557.027 298.2779572.008298.74369584.114299.85519632.537   305.59656.749306.6776
9691.655307.11389729.384 306.3839753.596306.59179777.807303.50239801.434 299.248
9813.187296.24049836.693289.39849857.496284.30879882.295275.81489893.584272.4617
9904.356269.94849915.091265.76999936.145249.92229956.602241.6047 9976.62239.0391
9986.665233.22789996.729230.719410006.83232.295510016.93236.902310036.96238.1968
10067.41243.784410098.97 247.47210109.76248.120710131.32246.732810137.16246.8762
#Mann= 3 , 0 , 0
9557.027    0.04       09557.027    0.04       010137.16    0.04       0
#XS Ineff= 2 , 0
       0                10122.09       0
Bank Sta=9557.027,10137.16
Exp/Cntr=0.3,0.1

Type RM Length L Ch R = 1 ,5121.726,140.120900,140.120900,140.120900
XS GIS Cut Line= 6
818435.806884214787484.581291615818570.295924068787364.152291523
818758.641526526787169.810013696818816.885627331787117.103934728
818956.807471795787024.200030002819125.682060516786938.176558965
#Sta/Elev= 30
9556.262 302.9519570.909304.97149616.769306.61069702.282302.51559735.574303.0775
9778.196 292.4229836.011288.87339842.279287.78089848.782284.33369871.338268.8604
9885.868  261.479914.927 254.5199931.487246.97339972.839241.84649987.575229.6888
10002.26230.400910030.08242.184510043.46243.984810070.44244.624110083.59243.9737
10096.07241.239710120.72238.662910181.56238.090910216.79240.852310252.01238.5339
10274.79 239.65810308.85235.395410320.21 236.46710365.21232.6374 10443.7232.2433
#Mann= 3 , 0 , 0
9556.262    0.04       09556.262    0.04       0 10443.7    0.04       0
#XS Ineff= 2 , 0
       0                 10077.9       0
Bank Sta=9556.262,10443.7
Exp/Cntr=0.3,0.1

Type RM Length L Ch R = 1 ,4981.605,140.120900,140.120900,140.120900
XS GIS Cut Line= 6
  818574.5110852787599.012519919818766.507120653787400.862458666
818893.076600919787208.506205121818944.939745307787148.711709542
819055.766078485787063.327044947819201.048744622786981.738524323
#Sta/Elev= 30
9553.631312.0224 9581.75311.41369595.475309.54129617.894308.63769622.923307.9659
 9650.85299.87539660.817298.55119689.012298.76049716.665296.93899829.742295.8983
9837.219294.03589843.426290.49699849.973 285.2259859.538278.81019899.821258.0989
9924.089243.48449935.708239.24529947.327232.70449958.946229.73619987.908 228.505
10052.55229.017810079.65230.696810125.07231.630310179.35 231.49910192.59230.7221
 10382.8230.862310394.13232.257210405.46237.136110416.79238.443110446.31238.8134
#Mann= 3 , 0 , 0
9553.631    0.06       09553.631    0.06       010446.31    0.06       0
#XS Ineff= 2 , 0
       0                 10051.2       0
Bank Sta=9553.631,10446.31
Exp/Cntr=0.3,0.1

Type RM Length L Ch R = 1 ,4841.484,140.121000,140.121000,140.121000
XS GIS Cut Line= 6
818650.542135697787635.922451078818863.958783182787430.363560953
818974.164678765787340.218941243819008.913371125787308.103871582
819169.189289782787193.830629172819349.649817187787087.223696338
#Sta/Elev= 30
9553.637300.63079601.479299.56699615.363296.28959643.132 296.1429712.553293.4221
9771.191292.91339795.858294.62599800.021293.35069823.627275.93159837.511267.2852
9843.266262.04149864.631240.13039877.927232.60419891.223228.91389968.156228.3677
10061.74230.361310084.88231.517910111.87239.012910122.32243.8055 10134.8251.4213
10159.02251.156910171.13251.880710183.23253.788410195.34254.169310216.91256.5739
10243.56260.449910255.31260.966910337.54269.295910372.07270.109210446.36 273.543
#Mann= 3 , 0 , 0
9553.637  0.0666       09553.637  0.0666       010446.36  0.0666       0
#XS Ineff= 2 , 0
       0                10086.76       0
Bank Sta=9553.637,10446.36
Exp/Cntr=0.3,0.1

Type RM Length L Ch R = 1 ,4701.363,140.120900,140.120900,140.120900
XS GIS Cut Line= 6
818688.894353616 787750.59960746818895.710739295787567.671604469
819046.927652581787449.264681579819078.994345077787427.971760751
819286.055239064787300.034798315819408.581549681787226.862321459
#Sta/Elev= 30
9553.613301.44589562.065301.71329577.159298.0888 9622.44296.16759655.217292.6314
9682.815292.72449815.422287.14349841.702289.97169849.785287.18129854.599283.4256
9867.497270.9717 9893.08249.59889905.703236.09849914.163229.94729918.325 228.828
9930.551228.423910031.48227.959510067.35229.9477 10079.1234.377310090.86240.6966
10102.61 244.80710149.63245.463910218.14250.940210243.67255.564810278.93 257.373
10290.69260.164510302.44259.9212 10337.4264.073710411.02269.0296 10446.4 270.397
#Mann= 3 , 0 , 0
9553.613  0.0689       09553.613  0.0689       0 10446.4  0.0689       0
#XS Ineff= 2 , 0
       0                               0
Bank Sta=9553.613,10446.4
Exp/Cntr=0.3,0.1

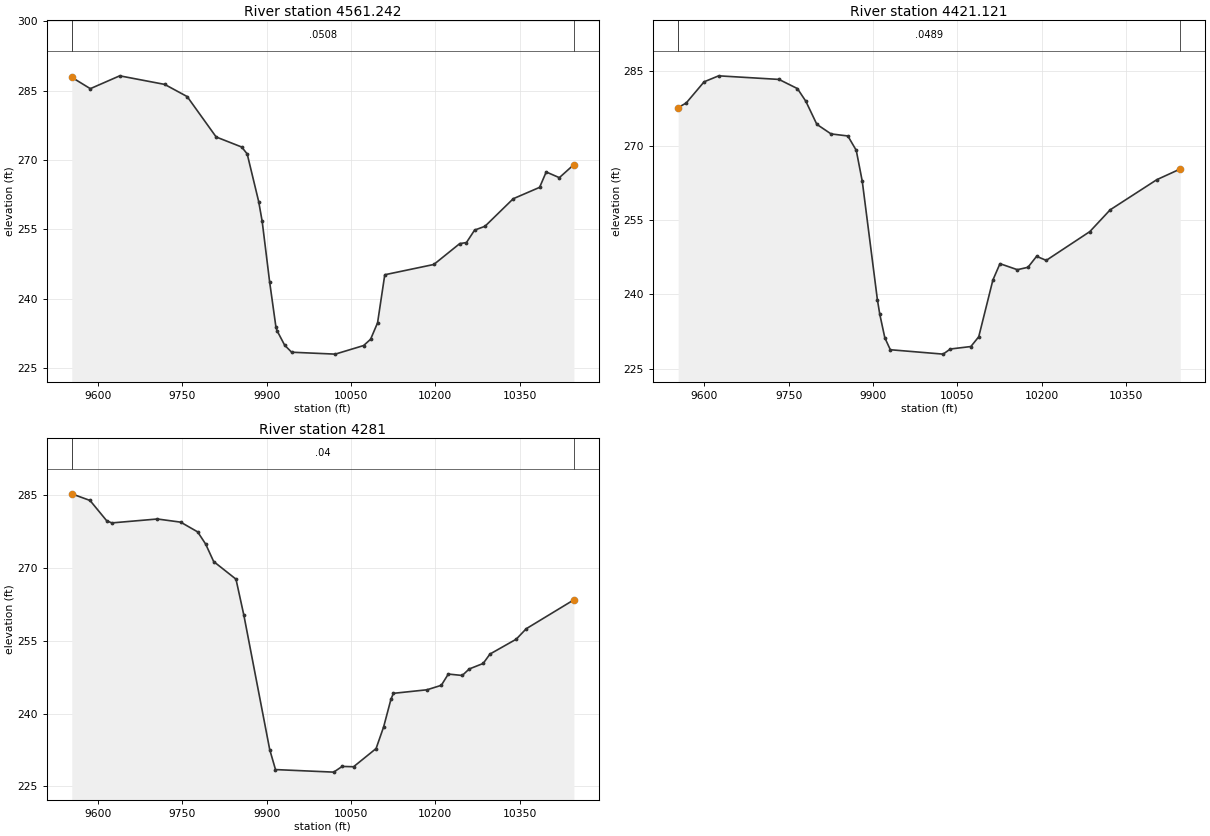
Type RM Length L Ch R = 1 ,4561.242,140.121000,140.121000,140.121000
XS GIS Cut Line= 6
818779.748733157787863.265651721818842.952685786787810.209639755
819043.477334713787633.431276111819160.849188776787537.687831188
819304.289770141 787436.17586206819487.145169404787321.760807708
#Sta/Elev= 30
  9553.6287.90969586.569285.4484 9638.85288.23029718.837286.3729 9758.83283.7336
9810.339274.98719855.705272.81549865.479271.32179885.948260.99579892.141256.7214
9905.427243.57789916.587233.84139918.462233.06539932.177229.88969944.532228.3832
10022.04227.968110072.49229.8249 10084.9231.188110097.31234.748210110.12245.1557
10197.34247.380610243.41251.8992 10255.3252.125310269.81 254.819 10288.3255.6519
10338.54261.619710385.44264.082110397.13267.411610420.51 266.181 10446.4 269.012
#Mann= 3 , 0 , 0
  9553.6  0.0508       0  9553.6  0.0508       0 10446.4  0.0508       0
#XS Ineff= 2 , 0
       0                               0
Bank Sta=9553.6,10446.4
Exp/Cntr=0.3,0.1

Type RM Length L Ch R = 1 ,4421.121,140.120900,140.120900,140.120900
XS GIS Cut Line= 6
818869.353721825787974.060474249818933.132367857787921.714373399
 819138.17159135787736.952500246819244.843413349787649.565119236
819405.741547243787530.300972066819570.431685564787423.971252517
#Sta/Elev= 30
9553.618277.6827  9567.9278.60399599.733282.87929625.607284.08639732.869283.3611
9765.665281.50949780.603278.95269800.174274.29569825.418272.36419855.295271.9501
9870.233269.0506 9880.94262.80059907.862238.86979912.132235.93239921.021231.2308
9930.798228.813410024.69227.926910037.46228.958310074.02229.460710087.99231.4236
10113.16242.877710125.75246.179610156.64244.965910175.53245.4501 10190.9247.6641
10208.03246.843910285.56252.655710321.68257.045810404.66263.1324 10446.4265.2938
#Mann= 3 , 0 , 0
9553.618  0.0489       09553.618  0.0489       0 10446.4  0.0489       0
#XS Ineff= 2 , 0
       0                               0
Bank Sta=9553.618,10446.4
Exp/Cntr=0.3,0.1

Type RM Length L Ch R = 1 ,    4281,0.000000,0.000000,0.000000
XS GIS Cut Line= 6
818968.897260946788092.900968868819058.413516001 788020.06297804
819309.014326175787774.604218143819379.072182119787712.466822429
819517.200993781787606.389169341819650.209613356787519.996769513
#Sta/Elev= 30
9553.619 285.3419586.075283.97039615.768279.77959624.891279.34199705.841280.1496
9747.289279.4969 9777.42277.48969791.655274.97799805.891271.37419845.576267.7377
9859.627260.28339905.541232.58469915.828228.459210019.34227.933210034.38229.1118
10054.64229.042610094.66232.795310108.11237.272810121.14242.9847 10125.5244.1871
10185.17244.918710210.67245.843210223.06248.164410247.85247.871410260.24 249.213
10285.02250.346810297.16252.289110343.78255.351210361.63 257.51310446.38263.4798
#Mann= 3 , 0 , 0
9553.619    0.04       09553.619    0.04       010446.38    0.04       0
#XS Ineff= 2 , 0
       0                               0
Bank Sta=9553.619,10446.38
Exp/Cntr=0.3,0.1